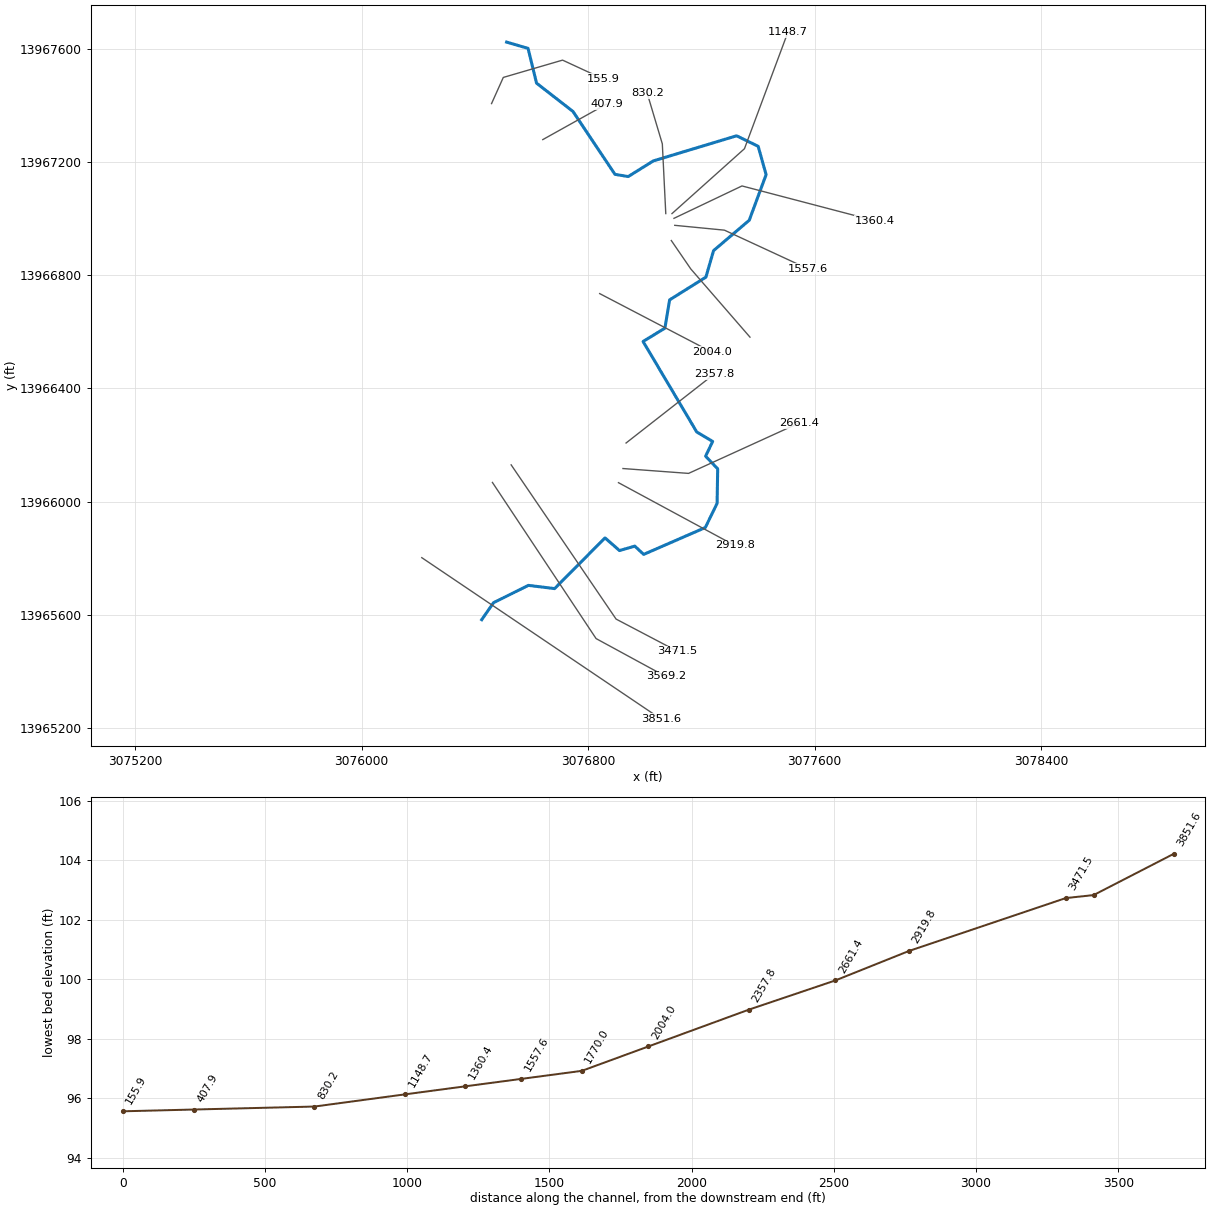
--- M101-00-00.prj (project) ---

Proj Title=M101-00-00
Current Plan=p02
Default Exp/Contr=.3,.1
English Units
Geom File=g01
Flow File=f01
Flow File=f02
Plan File=p01
Plan File=p02
Y Axis Title=Elevation
X Axis Title(PF)=Main Channel Distance
X Axis Title(XS)=Station
BEGIN DESCRIPTION:
Willow Creek
Tributary 0.26 to Willow Creek
HCFCD Unit M101-00-00
Flood Hazard Model
10, 2, 1, 0.50-year Event
Filename M101-00-00.prj
Prepared by: Halff Associates, Inc. Date: 03/05/2004
Reviewed by:                  Date:
STATUS Final RAS
END DESCRIPTION:
DSS File=dss
DSS Export Rating Curves= 0
DSS Export Rating Curve Sorted= 0
DSS Export Volume Flow Curves= 0
DXF OffsetX= 0
DXF OffsetY= 0
DXF ScaleX= 1
DXF ScaleY= 10

--- M101-00-00.p02 (plan) ---

Plan Title=Floodway
Program Version=3.11
Short Identifier=Floodway0607
Geom File=g01
Flow File=f02
Subcritical Flow
K Sum by GR= 0
Std Step Tol= 0.01
Critical Tol= 0.01
Num of Std Step Trials= 20
Max Error Tol= 0.3
Flow Tol Ratio= 0.001
Split Flow NTrial= 30
Split Flow Tol= 0.02
Split Flow Ratio= 0.02
Log Output Level= 0
Friction Slope Method= 1
Unsteady Friction Slope Method= 2
Unsteady Bridges Friction Slope Method= 1
Parabolic Critical Depth
Global Vel Dist= 0 , 0 , 0
Global Log Level= 0
CheckData=True
Encroach Param=-1 ,0,0, 2
Encroach River=M101-00-00
Encroach Reach=M101-00-00_0002
Encroach Node=3851.6
       1    4935    5120
Encroach Node=3569.2
       1    4910    5045
Encroach Node=3471.5
       1    4937    5030
Encroach Node=2919.8
       1    4965    5020
Encroach Node=2661.4
       1    4978    5033
Encroach Node=2357.8
       1    4970    5015
Encroach Node=2004.0
       1    4955    5017
Encroach Node=1770.0
       1    4950    5015
Encroach Node=1557.6
       1    4970    5055
Encroach Node=1360.4
       1    4920    5029
Encroach Node=1148.7
       1    4930    5050
Encroach Node=830.2
       1    4965    5035
Encroach Node=407.9
       1    4952    5034
Encroach Node=155.9
       1    4950    5050
Computation Interval=1HOUR
Output Interval=1HOUR
Run HTab= 0
Run UNet= 0
Run PostProcess= 0
UNET Theta= 1
UNET Theta Warmup= 1
UNET ZTol= 0.02
UNET ZSATol= 0.1
UNET MxIter= 20
UNET MaxInSteps= 20
UNET DtIC= 0
UNET DtMin= 0
UNET MaxCRTS= 20
UNET WFStab= 2
UNET SFStab= 1
UNET WFX= 1
UNET SFX= 1
UNET DSS MLevel= 4
UNET DZMax Abort= 100
UNET Convert EG Bridges=-1
UNET Use Existing IB Tables=-1
UNET Froude Reduction=False
UNET Froude Limit= 1
UNET Froude Power= 10
Instantaneous Interval=1HOUR
DSS File=dss
Write IC File= 0
Echo Input=False
Echo Output=False
Write Detailed= 0
Detailed Automatic Start=False, 10

--- M101-00-00.p01 (plan) ---

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Plan Title=FEMA Effective June 2007
Program Version=3.13
Short Identifier=FEMAeff0607
Geom File=g01
Flow File=f01
Encroach Param=-1 ,0,0, 0

--- M101-00-00.f02 (steady flow) ---

Flow Title=Floodway
Program Version=3.13
Number of Profiles= 2
Profile Names=1PCT_100yr,1PCTFloodway_100yrFW
River Rch & RM=M101-00-00,M101-00-00_0002       ,3851.6
    1155    1155
Boundary for River Rch & Prof#=M101-00-00,M101-00-00_0002       , 1
Up Type= 0
Dn Type= 3
Dn Slope=0.005
Boundary for River Rch & Prof#=M101-00-00,M101-00-00_0002       , 2
Up Type= 0
Dn Type= 1
Dn Known WS=105.49
DSS Import GetInterval= 0
DSS Import GetPeak= 0
DSS Import FillOption= 0

--- M101-00-00.f01 (steady flow) ---

Flow Title=FEMA Effective June 2007
Program Version=3.13
Number of Profiles= 4
Profile Names=10PCT_10yr, 2PCT_50yr, 1PCT_100yr,0.2PCT_500yr
River Rch & RM=M101-00-00,M101-00-00_0002 ,3851.6
     608     973    1155    1698
Boundary for River Rch & Prof#=M101-00-00,M101-00-00_0002 , 1
Up Type= 0
Dn Type= 3
Dn Slope=0.005
Boundary for River Rch & Prof#=M101-00-00,M101-00-00_0002 , 2
Up Type= 0
Dn Type= 3
Dn Slope=0.005
Boundary for River Rch & Prof#=M101-00-00,M101-00-00_0002 , 3
Up Type= 0
Dn Type= 3
Dn Slope=0.005
Boundary for River Rch & Prof#=M101-00-00,M101-00-00_0002 , 4
Up Type= 0
Dn Type= 3
Dn Slope=0.005
DSS Import GetInterval= 0
DSS Import GetPeak= 0
DSS Import FillOption= 0

--- M101-00-00.g01 (geometry) ---

Geom Title=M101-00-00 June 2007
Program Version=3.13

River Reach=M101-00-00      ,M101-00-00_0002
Reach XY= 30
       3076512.5     13967622.87       3076588.2     13967600.77
      3076618.26     13967477.89      3076746.74     13967378.06
      3076895.17     13967155.84      3076942.05     13967148.03
      3077030.76     13967203.24      3077324.89     13967291.99
      3077400.98     13967254.78      3077429.09     13967154.71
      3077369.49     13966993.68      3077243.45     13966886.39
      3077216.37     13966792.64      3077088.24     13966712.43
      3077071.57     13966612.43      3076994.49     13966565.55
      3077184.07     13966245.76      3077240.32     13966212.43
      3077215.32     13966160.34      3077258.03     13966115.55
      3077255.95     13965993.68      3077214.28     13965908.26
      3076996.57     13965813.47      3076965.32     13965842.64
      3076911.16     13965827.01      3076860.12      13965871.8
      3076681.99     13965692.64      3076589.28     13965704.09
       3076466.2     13965642.77      3076424.56     13965582.75

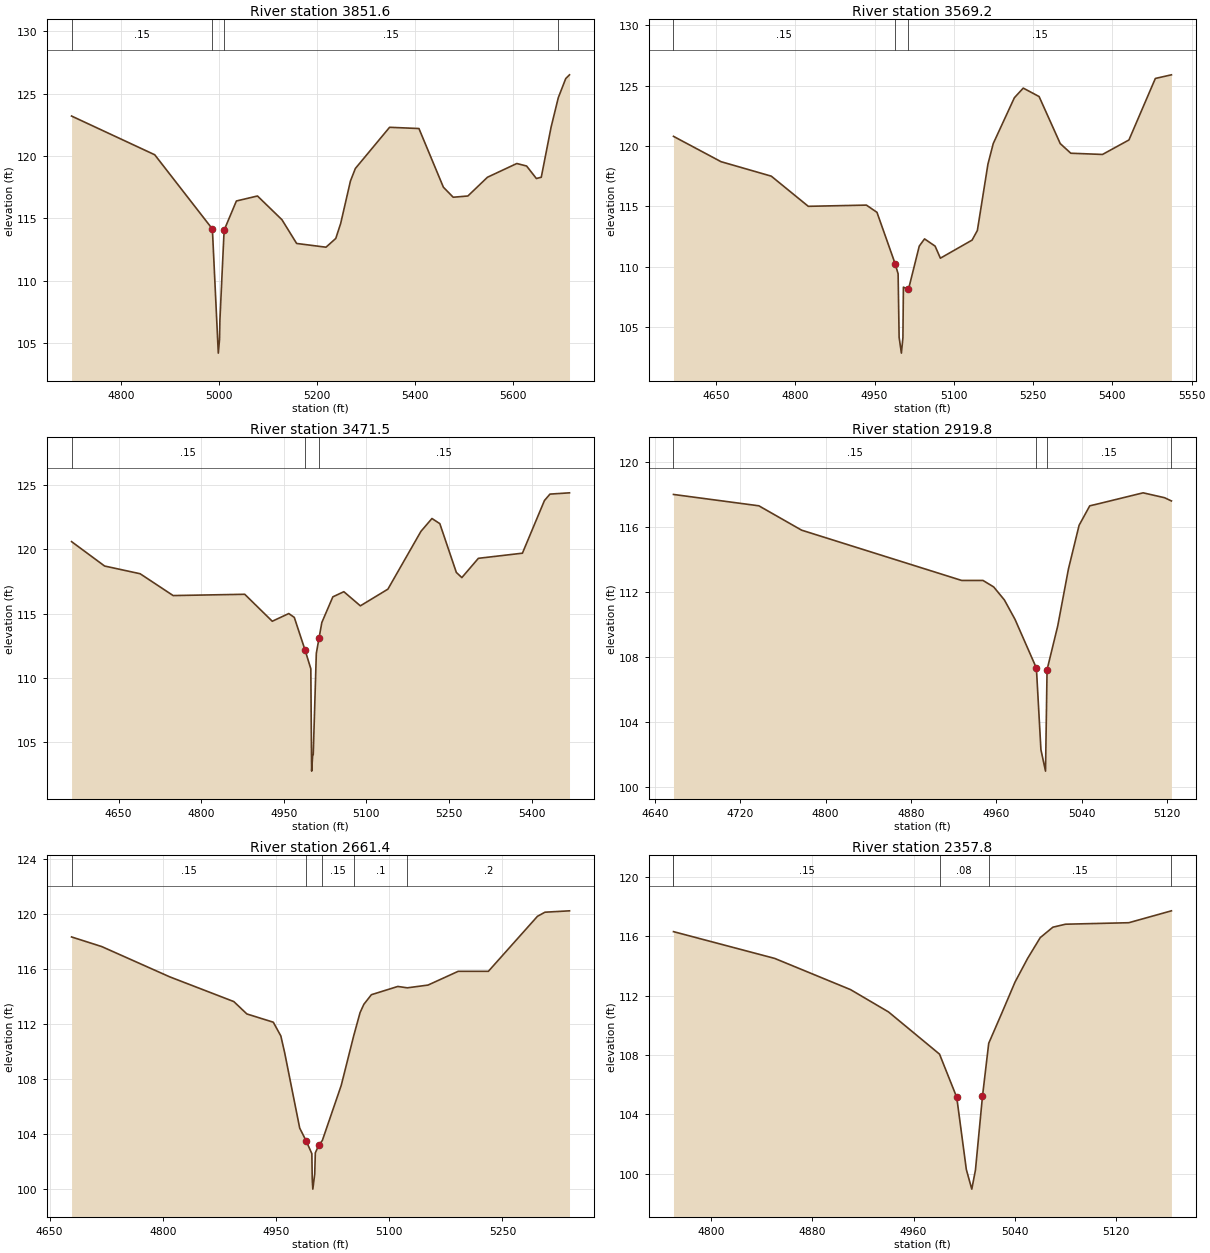
Type RM Length L Ch R = 1 ,3851.6  ,202.3,282.4,162.1
BEGIN DESCRIPTION:
Cross Section 3851.6
Cross Section XS04
END DESCRIPTION:
XS GIS Cut Line= 2
      3076212.93      13965801.9      3077056.63      13965232.8
#Sta/Elev= 30
  4698.8   123.2  4868.8   120.1  4986.6  114.16  4998.7  104.22  5001.2  105.32
    5002  106.86  5010.6  114.06  5035.7   116.4  5078.8   116.8  5128.8   114.9
  5158.8     113  5218.8   112.7  5238.8   113.4  5248.8   114.6  5268.8     118
  5278.8     119  5348.8   122.3  5408.8   122.2  5458.8   117.5  5478.8   116.7
  5508.8   116.8  5548.8   118.3  5608.8   119.4  5628.8   119.2  5648.8   118.2
  5658.8   118.3  5678.8   122.3  5693.6  124.67  5708.8   126.2  5716.5   126.5
#Mann= 4 ,-1 , 0
  4698.8     .15       0  4986.6     .08       0  5010.6     .15       0
  5693.6      .2       0
#XS Ineff= 2 , 0
       0                    5400       0     120
Permanent Ineff=
       F       F
Bank Sta=4986.6,5010.6
Exp/Cntr=0.3,0.1

Type RM Length L Ch R = 1 ,3569.2  ,94.6,97.7,96.5
BEGIN DESCRIPTION:
Cross Section 3569.2
END DESCRIPTION:
XS GIS Cut Line= 4
       3076462.4      13966067.6      3076531.58      13965963.4
      3076828.54      13965516.1       3077074.8      13965382.2
#Sta/Elev= 30
  4569.4   120.8  4659.4   118.7  4754.5   117.5  4824.5     115  4934.5   115.1
  4954.5   114.5  4988.8  110.25  4994.5   109.4  4996.4  104.15  5000.7  102.83
  5003.6  104.11  5004.5   108.3  5014.1  108.11  5034.5   111.7  5044.5   112.3
  5064.5   111.7  5074.5   110.7  5134.5   112.2  5144.5     113  5164.5   118.5
  5174.5   120.2  5214.5     124  5231.3   124.8  5261.3   124.1  5301.3   120.2
  5321.3   119.4  5381.3   119.3  5431.3   120.5  5481.3   125.6  5511.7   125.9
#Mann= 3 ,-1 , 0
  4569.4     .15       0  4988.8     .08       0  5014.1     .15       0
Bank Sta=4988.8,5014.1
Exp/Cntr=0.3,0.1

Type RM Length L Ch R = 1 ,3471.5  ,475.7,551.7,479.2
BEGIN DESCRIPTION:
Cross Section 3471.5
END DESCRIPTION:
XS GIS Cut Line= 4
      3076528.56      13966129.7      3076598.57      13966026.8
      3076899.15       13965585.      3077116.44      13965470.9
#Sta/Elev= 30
  4564.7   120.6  4624.7   118.7  4689.2   118.1  4749.2   116.4  4879.2   116.5
  4929.2   114.4  4959.2     115  4969.2   114.7  4988.8  112.15  4999.2   110.7
  5000.7  102.73  5002.6  103.99  5003.6  104.01  5009.2   111.9  5014.1  113.08
  5019.2   114.3  5039.2   116.3  5059.2   116.7  5089.2   115.6  5139.2   116.9
  5199.2   121.4  5219.2   122.4  5233.5     122  5263.5   118.2  5273.5   117.8
  5303.5   119.3  5383.5   119.7  5423.5   123.8  5433.5   124.3    5469   124.4
#Mann= 3 ,-1 , 0
  4564.7     .15       0  4988.8     .08       0  5014.1     .15       0
Bank Sta=4988.8,5014.1
Exp/Cntr=0.3,0.1

Type RM Length L Ch R = 1 ,2919.8  ,230.5,258.4,275.5
BEGIN DESCRIPTION:
Cross Section 2919.8
Cross Section XS3.7
END DESCRIPTION:
XS GIS Cut Line= 2
       3076907.6      13966066.8      3077318.11      13965845.1
#Sta/Elev= 22
  4657.5     118  4737.5   117.3  4777.5   115.8  4927.5   112.7  4947.5   112.7
  4957.5   112.3  4967.5   111.5  4977.5   110.3 4980.55  109.84  4997.5   107.3
 5001.75  102.27 5006.05  100.95  5007.5   107.2  5017.5   109.9 5019.45  110.58
  5027.5   113.4  5037.5   116.1  5047.5   117.3  5052.8  117.38  5097.5   118.1
  5117.5   117.8    5124   117.6
#Mann= 4 ,-1 , 0
  4657.5     .15       0  4997.5     .08       0  5007.5     .15       0
    5124      .2       0
Bank Sta=4997.5,5007.5
Exp/Cntr=0.3,0.1

Type RM Length L Ch R = 1 ,2661.4  ,241.9,303.6,257.8
BEGIN DESCRIPTION:
Cross Section 2661.4
Cross Section XS8.5
END DESCRIPTION:
XS GIS Cut Line= 3
      3076923.45     13966116.72      3077155.11     13966099.56
      3077544.07     13966276.88
#Sta/Elev= 30
    4679   118.3    4719   117.6    4809   115.4    4894   113.6  4911.3   112.7
  4946.3   112.1  4956.3   111.1  4961.3   109.9  4981.3   104.4 4989.73  103.48
  4997.4  102.54  4997.9  100.72  4998.7   99.96  5001.2  101.06    5002   102.6
 5006.58  103.15  5011.3   103.5  5036.3   107.5  5052.8   111.1  5061.3   112.8
  5066.3   113.4  5076.3   114.1  5111.3   114.7    5124   114.6  5151.3   114.8
  5191.3   115.8  5231.3   115.8  5296.3   119.8  5306.3   120.1  5338.8   120.2
#Mann= 5 ,-1 , 0
    4679     .15       0 4989.73     .08       0  5011.3     .15       0
  5052.8      .1       0    5124      .2       0
Bank Sta=4989.73,5006.58
Exp/Cntr=0.3,0.1

Type RM Length L Ch R = 1 ,2357.8  ,382.88,353.8,298.04
BEGIN DESCRIPTION:
Cross Section 2357.8
Cross Section XS3.5
END DESCRIPTION:
XS GIS Cut Line= 2
      3076934.43      13966206.9      3077244.56      13966449.5
#Sta/Elev= 19
  4770.2   116.3  4850.2   114.5  4910.2   112.4  4940.2   110.9 4980.55  108.06
 4994.15  105.16 5001.75   100.3 5006.05   98.98 5008.95  100.26 5014.52  105.23
 5019.45  108.79  5030.2   110.9  5040.2   112.9  5050.2   114.5  5060.2   115.9
  5070.2   116.6  5080.2   116.8  5130.2   116.9  5163.9   117.7
#Mann= 5 , 1 , 0
  4770.2      .2       0  4770.2     .15       0 4980.55     .08       0
 5019.45     .15       0  5163.9      .2       0
Bank Sta=4994.15,5014.52
Exp/Cntr=0.3,0.1

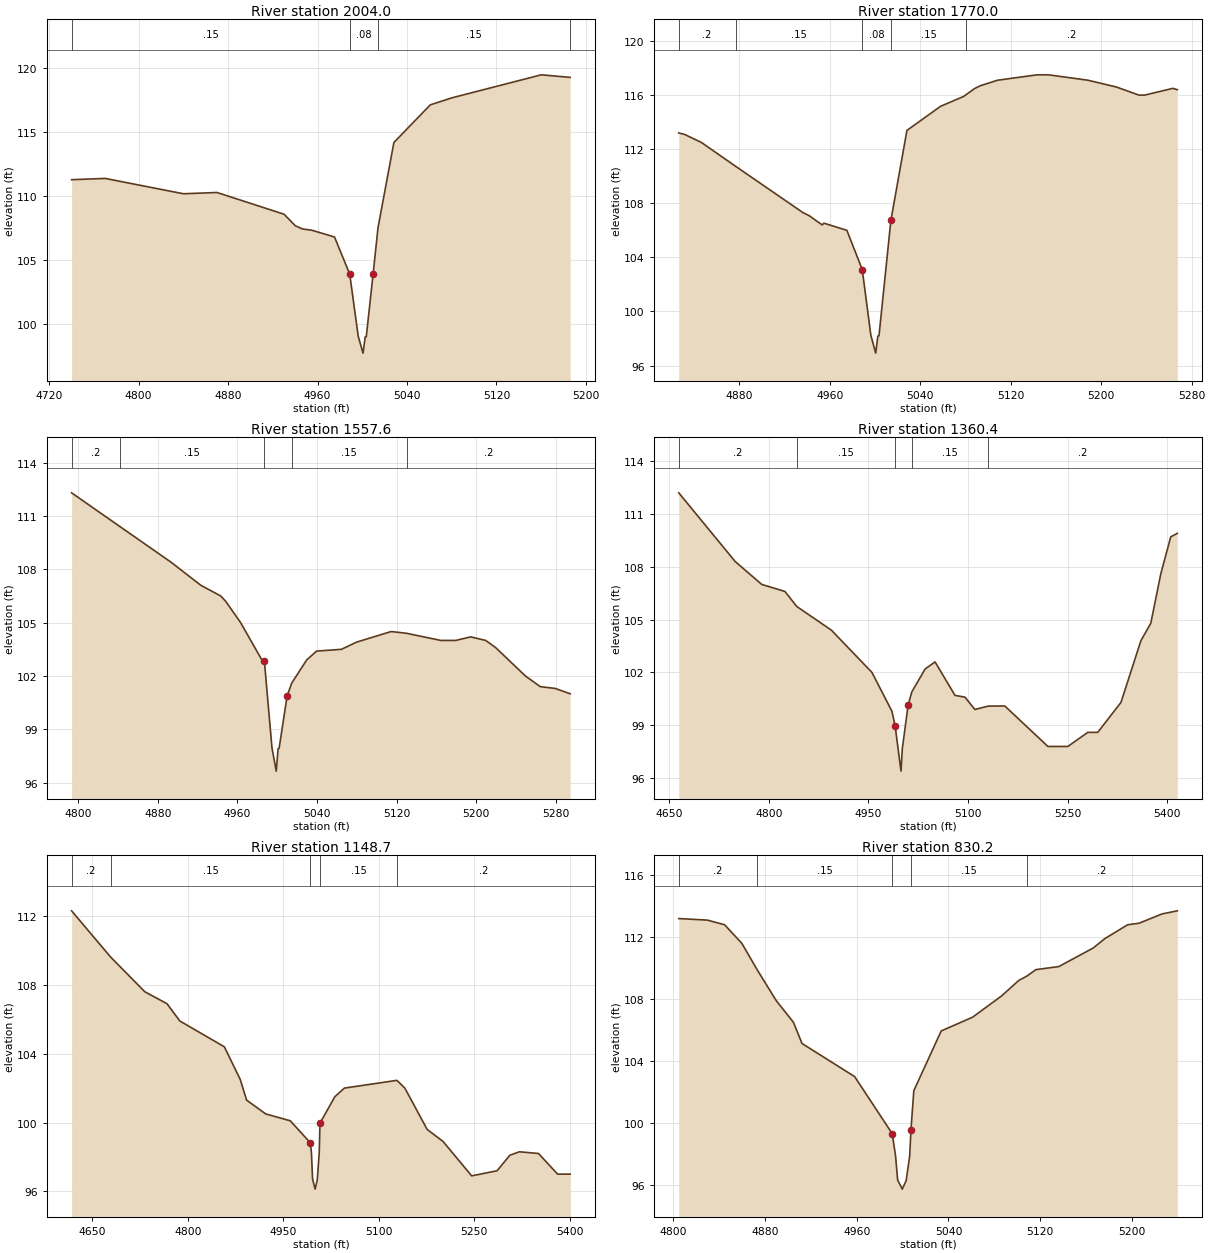
Type RM Length L Ch R = 1 ,2004.0  ,233.1,234,215.5
BEGIN DESCRIPTION:
Cross Section XS3.3
END DESCRIPTION:
XS GIS Cut Line= 2
      3076841.24      13966734.6      3077236.47      13966528.5
#Sta/Elev= 21
  4740.1   111.3  4770.1   111.4  4840.1   110.2  4870.1   110.3  4930.1   108.6
  4940.1   107.7 4946.45  107.45  4954.9  107.35  4975.2  106.82  4988.8  103.92
  4996.4   99.06  5000.7   97.74  5002.6      99  5003.6   99.02 5009.68   103.9
  5014.1  107.55  5028.3  114.21 5060.82  117.15  5080.1   117.7  5160.1   119.5
  5185.9   119.3
#Mann= 4 ,-1 , 0
  4740.1     .15       0  4988.8     .08       0  5014.1     .15       0
  5185.9      .2       0
Bank Sta=4988.8,5009.68
Exp/Cntr=0.3,0.1

Type RM Length L Ch R = 1 ,1770.0  ,190,212.4,218
BEGIN DESCRIPTION:
Cross Section 1770.0
Cross Section XS03
END DESCRIPTION:
XS GIS Cut Line= 3
      3077094.18      13966922.1      3077163.05     13966821.65
      3077372.11     13966580.78
#Sta/Elev= 30
  4826.6   113.2  4831.6   113.1  4846.6   112.5  4876.8  110.74  4936.6   107.3
  4941.6   107.1  4953.4   106.4  4954.9  106.53  4975.2     106  4988.8   103.1
  4996.4   98.24  5000.7   96.92  5002.6   98.18  5003.6    98.2  5014.1  106.73
  5028.3  113.39 5057.98  115.17  5078.4   115.9  5080.7  116.04  5088.4   116.5
  5093.4   116.7  5108.4   117.1  5143.4   117.5  5153.4   117.5  5188.4   117.1
  5213.4   116.6  5233.4     116  5238.4     116  5263.4   116.5  5267.3   116.4
#Mann= 5 ,-1 , 0
  4826.6      .2       0  4876.8     .15       0  4988.8     .08       0
  5014.1     .15       0  5080.7      .2       0
Bank Sta=4988.8,5014.1
Exp/Cntr=0.3,0.1

Type RM Length L Ch R = 1 ,1557.6  ,152.4,197.2,198.7
BEGIN DESCRIPTION:
Right ineffective at drainage area divide
Cross Section 1557.6
Cross Section XS2.5
END DESCRIPTION:
XS GIS Cut Line= 3
      3077106.37     13966975.74      3077281.91     13966958.67
       3077576.9     13966822.14
#Sta/Elev= 30
  4793.2   112.3  4841.9   110.4  4893.2   108.4  4923.2   107.1  4943.2   106.5
  4948.2   106.2  4963.2     105  4984.6   102.9  4987.1  102.83  4994.7   97.97
    4999   96.65  5000.9   97.91  5001.9   97.93 5009.95  100.88  5014.6   101.6
  5029.6   102.9  5039.6   103.4  5064.6   103.5  5079.6   103.9  5114.6   104.5
  5130.1   104.4  5164.6     104  5179.6     104  5194.6   104.2  5209.6     104
  5219.6   103.6  5249.6     102  5264.6   101.4  5279.6   101.3  5294.6     101
#Mann= 5 ,-1 , 0
  4793.2      .2       0  4841.9     .15       0  4987.1     .08       0
  5014.6     .15       0  5130.1      .2       0
#XS Ineff= 2 , 0
       0                    5145       0
Permanent Ineff=
       F       F
Bank Sta=4987.1,5009.95
Exp/Cntr=0.3,0.1

Type RM Length L Ch R = 1 ,1360.4  ,96.4,211.7,275.2
BEGIN DESCRIPTION:
Right ineffective at drainage area divide
Cross Section 1360.4
Cross Section XS4.5
END DESCRIPTION:
XS GIS Cut Line= 3
      3077103.63     13967000.46      3077343.87     13967114.86
      3077812.91     13966991.88
#Sta/Elev= 30
  4664.2   112.2  4749.2   108.3  4789.2     107  4824.2   106.6  4841.9  105.75
  4894.2   104.4  4955.3     102  4985.3    99.8 4990.09   98.98    4999    96.4
  5000.9   97.66 5009.72  100.15  5015.3   100.9  5035.3   102.2  5050.3   102.6
  5080.3   100.7  5095.3   100.6  5110.3    99.9  5130.1  100.09  5155.3   100.1
  5220.3    97.8  5250.3    97.8  5280.3    98.6  5295.3    98.6  5330.3   100.3
  5360.3   103.8  5375.3   104.8  5390.3   107.6  5405.3   109.7  5415.2   109.9
#Mann= 5 ,-1 , 0
  4664.2      .2       0  4841.9     .15       0 4990.09     .08       0
  5015.3     .15       0  5130.1      .2       0
#XS Ineff= 2 , 0
       0                    5060       0
Permanent Ineff=
       F       F
Bank Sta=4990.09,5009.72
Exp/Cntr=0.3,0.1

Type RM Length L Ch R = 1 ,1148.7  ,209.8,318.5,344.2
BEGIN DESCRIPTION:
Right ineffective at drainage area divide
Cross Section 1148.7
Cross Section XS2.3
END DESCRIPTION:
XS GIS Cut Line= 3
      3077096.62     13967017.18      3077352.61     13967246.35
       3077506.2     13967658.37
#Sta/Elev= 30
  4617.4   112.3  4678.6  109.62  4732.4   107.6  4767.4   106.9  4787.4   105.9
  4857.4   104.4  4882.4   102.5  4892.4   101.3  4922.4   100.5    4961   100.1
 4992.53   98.82  4994.2   98.26    4996   96.72    5000   96.13  5003.4   96.67
  5006.5   98.26  5007.6   99.96    5031   101.5    5046     102  5128.5  102.45
    5141     102    5176    99.6    5201    98.9    5246    96.9    5286    97.2
    5306    98.1    5321    98.3    5351    98.2    5381      97  5400.7      97
#Mann= 5 ,-1 , 0
  4617.4      .2       0  4678.6     .15       0 4992.53     .08       0
  5007.6     .15       0  5128.5      .2       0
#XS Ineff= 2 , 0
       0                    5110       0
Permanent Ineff=
       F       F
Bank Sta=4992.53,5007.6
Exp/Cntr=0.3,0.1

Type RM Length L Ch R = 1 ,830.2   ,459.9,422.3,341.7
BEGIN DESCRIPTION:
Cross Section 830.2
Cross Section XS02
END DESCRIPTION:
XS GIS Cut Line= 3
      3077074.68     13967017.18      3077062.49     13967263.42
      3077008.85       13967443.
#Sta/Elev= 30
  4804.8   113.2  4829.8   113.1  4844.8   112.8  4859.8   111.6  4873.3  109.88
  4889.8   107.9  4904.8   106.5  4912.3  105.13  4958.2  102.99    4991    99.3
  4993.9   97.85  4995.7   96.31  4999.7   95.72  5003.1   96.26  5006.2   97.85
  5007.3   99.55  5009.8  102.08  5033.7  105.94  5061.1  106.83  5086.3   108.2
  5101.3   109.2  5108.3  109.48  5116.3   109.9  5136.3   110.1  5166.3   111.3
  5176.3   111.9  5196.3   112.8  5206.3   112.9  5226.3   113.5  5239.6   113.7
#Mann= 5 ,-1 , 0
  4804.8      .2       0  4873.3     .15       0    4991     .08       0
  5007.3     .15       0  5108.3      .2       0
Bank Sta=4991,5007.3
Exp/Cntr=0.3,0.1

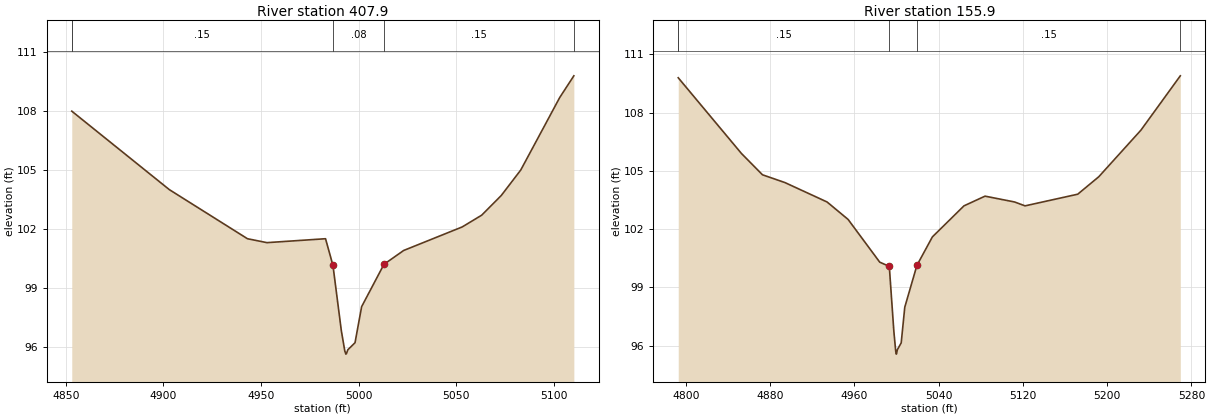
Type RM Length L Ch R = 1 ,407.9   ,252.48,252,223.89
BEGIN DESCRIPTION:
Cross Section 407.9
Cross Section XS1.5
END DESCRIPTION:
XS GIS Cut Line= 2
      3076640.21      13967278.5      3076864.85      13967403.7
#Sta/Elev= 23
  4853.1     108  4903.1     104  4943.1   101.5  4953.1   101.3  4983.1   101.5
  4986.9  100.14  4991.2   96.81    4993   95.76  4993.1   95.75  4993.5   95.62
  4993.8   95.64  4994.5   95.84  4998.2    96.2  5001.6   98.04    5013  100.19
  5013.1   100.2  5023.1   100.9  5053.1   102.1  5063.1   102.7  5073.1   103.7
  5083.1     105  5103.1   108.7  5110.3   109.8
#Mann= 5 , 1 , 0
  4853.1      .2       0  4853.1     .15       0  4986.9     .08       0
    5013     .15       0  5110.3      .2       0
Bank Sta=4986.9,5013
Exp/Cntr=0.3,0.1

Type RM Length L Ch R = 1 ,155.9   ,0,0,0
BEGIN DESCRIPTION:
Cross Section 155.9
Cross Section XS01
END DESCRIPTION:
XS GIS Cut Line= 4
     3076459.311    13967405.735     3076500.821     13967498.13
     3076710.113    13967559.251     3076852.931    13967493.206
#Sta/Elev= 26
  4792.7   109.8  4852.7   105.9  4872.7   104.8    4894   104.4    4934   103.4
    4954   102.5    4984   100.3  4993.1  100.08  4997.4   96.75  4999.2    95.7
  4999.3   95.69  4999.7   95.56    5000   95.58  5000.7   95.78  5004.4   96.14
  5007.8   97.98  5019.3  100.13    5034   101.6    5064   103.2    5084   103.7
    5112   103.4    5122   103.2    5172   103.8    5192   104.7    5232   107.1
  5269.4   109.9
#Mann= 5 , 1 , 0
  4792.7      .2       0  4792.7     .15       0  4993.1     .08       0
  5019.3     .15       0  5269.4      .2       0
Bank Sta=4993.1,5019.3
Exp/Cntr=0.3,0.1

Chan Stop Cuts=-1
Use User Specified Reach Order=0
User Specified Reach Order=M101-00-00      ,Reach - 1